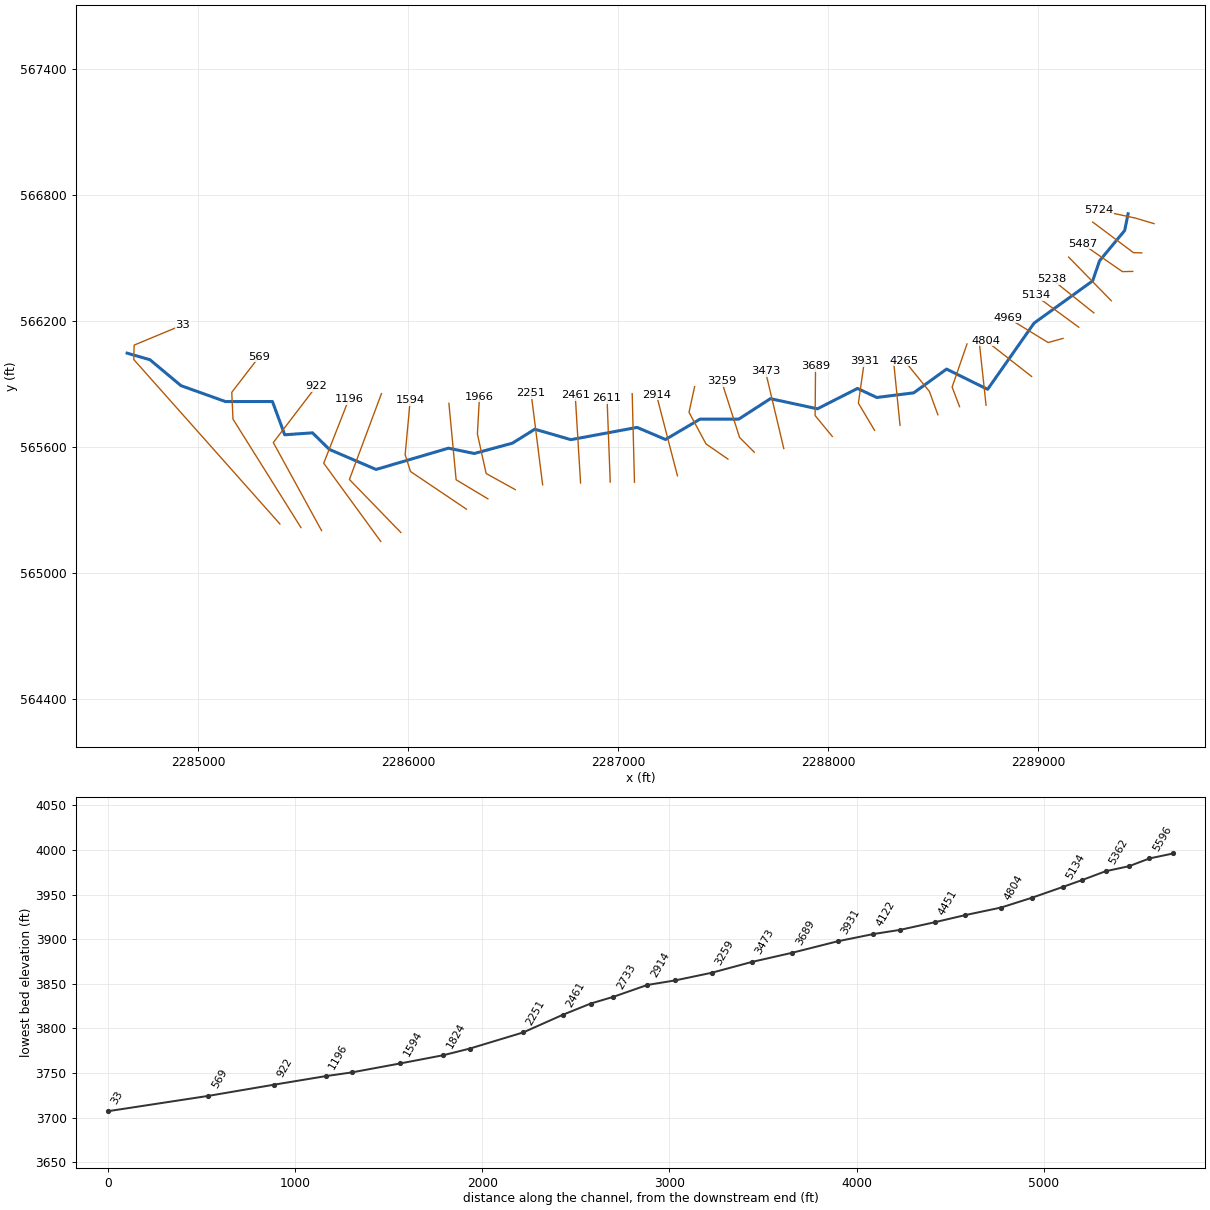
--- FIRSTFK_T1.prj (project) ---

Proj Title=FIRSTFK_T1
Current Plan=p01
Default Exp/Contr=0,0
English Units
Geom File=g01
Flow File=f01
Plan File=p01
BEGIN DESCRIPTION:
----------MODEL BY WOOD PLC 2022----------
AFH study
Randolph County, WV
HEC-RAS Version: RAS 6.2
Vertical Datum: NAVD88
Projection: NAD 1983 StatePlane West Virginia S FIPS 4702 (US Feet)
Terrain: 1-meter LIDAR (FEMA Region III 3DEP collected 2016-2018)
Land Use: 2019 NLCD
Hydrologic Method:
WV SIR2010-5033 regression equations
Additional Model Notes:
None
END DESCRIPTION:
DSS Export Rating Curves= 0
DSS Export Rating Curve Sorted= 0
DSS Export Volume Flow Curves= 0
DXF OffsetX= 0
DXF OffsetY= 0
DXF ScaleX= 0
DXF ScaleY= 0

--- FIRSTFK_T1.p01 (plan) ---

Plan Title=Floodplain
Program Version=6.20
Short Identifier=Floodplain
Geom File=g01
Flow File=f01
Subcritical Flow
K Sum by GR= 0
Std Step Tol= 0.01
Critical Tol= 0.01
Num of Std Step Trials= 20
Max Error Tol= 0.3
Flow Tol Ratio= 0.001
Split Flow NTrial= 30
Split Flow Tol= 0.02
Split Flow Ratio= 0.02
Log Output Level= 0
Friction Slope Method= 1
Unsteady Friction Slope Method= 2
Unsteady Bridges Friction Slope Method= 1
Parabolic Critical Depth
Global Vel Dist= 0 , 0 , 0
Global Log Level= 0
CheckData=True
Encroach Param=-1 ,0,0, 0
Mapping Interval=1HOUR
Computation Time Step Use Courant=        0
Computation Time Step Use Time Series=    0
Computation Time Step Count To Double=0
Computation Time Step Max Doubling=0
Computation Time Step Max Halving=0
Computation Time Step Residence Courant=0
Run HTab= 0
Run UNet= 0
Run Sediment= 0
Run PostProcess= 0
Run WQNet= 0
Run RASMapper=-1
UNET Theta= 0
UNET Theta Warmup= 0
UNET ZTol= 0
UNET ZSATol= 0
UNET MxIter= 0
UNET Max Iter WO Improvement= 0
UNET MaxInSteps= 0
UNET DtIC= 0
UNET DtMin= 0
UNET MaxCRTS= 0
UNET WFStab= 0
UNET SFStab= 0
UNET WFX= 1
UNET SFX= 1
UNET Gravity=32.174
UNET 1D Methodology=Finite Difference
UNET DSS MLevel= 1
UNET Pardiso=0
UNET DZMax Abort= 0
UNET Use Existing IB Tables= 0
UNET Froude Reduction=False
UNET Froude Limit= 0
UNET Froude Power= 0
UNET D1 Cores= 0
UNET WindReference=Eulerian
UNET WindDragFormulation=Hsu (1988)
UNET D2 Coriolis=0
UNET D2 Cores= 0
UNET D2 Theta= 1
UNET D2 Theta Warmup= 1
UNET D2 Z Tol= 0.01
UNET D2 Volume Tol= 0.01
UNET D2 Max Iterations= 20
UNET D2 Equation= 0
UNET D2 RampUpFraction=0.1
UNET D2 TimeSlices= 1
UNET D2 Turbulence Formulation=Non-Conservative (original)
UNET D2 Eddy Viscosity=0.3
UNET D2 Transverse Eddy Viscosity=0.1
UNET D2 Smagorinsky Mixing=0
UNET D2 BCVolumeCheck=0
UNET D2 Cores=0
UNET D2 SolverType=PARDISO (Direct)
UNET D2 Minimum Iterations= 2147483647
UNET D2 Maximum Iterations= 2147483647
UNET D2 Restart Number= 10
UNET D2 Relaxation Coeff=1.3
UNET D2 SOR Precondition Iterations= 10
UNET D2 ILUT Maximum Fill= 8
UNET D2 ILUT Tolerance=1E-08
UNET D1D2 MaxIter= 0
UNET D1D2 ZTol=0.01
UNET D1D2 QTol=0.1
UNET D1D2 MinQTol=1
Write IC File= 0
Write IC File at Fixed DateTime=0
Write IC File at Sim End=0
Echo Input=False
Echo Parameters=False
Echo Output=False
Write Detailed= 0
HDF Write Warmup=0
HDF Write Time Slices=0
HDF Flush=0
HDF Compression= 1
HDF Chunk Size= 1
HDF Spatial Parts= 1
HDF Use Max Rows=0
HDF Fixed Rows= 1
Calibration Method= 0
Calibration Iterations= 20
Calibration Max Change=0.05
Calibration Tolerance=0.2
Calibration Maximum=1.5
Calibration Minimum=0.5
Calibration Optimization Method= 1
WQ AD Non Conservative
WQ ULTIMATE=-1
WQ Max Comp Step=1HOUR
WQ Output Interval=15MIN
WQ Output Selected Increments= 0
WQ Output face flow=0
WQ Output face velocity=0
WQ Output face area=0
WQ Output face dispersion=0
WQ Output cell volume=0
WQ Output cell surface area=0
WQ Output cell continuity=0
WQ Output cumulative cell continuity=0
WQ Output face conc=0
WQ Output face dconc_dx=0
WQ Output face courant=0
WQ Output face peclet=0
WQ Output face adv mass=0
WQ Output face disp mass=0
WQ Output cell mass=0
WQ Output cell source sink temp=0
WQ Output nsm pathways=0
WQ Output nsm derived pathways=0
WQ Create Restart=0
WQ Fixed Restart=0
WQ System Summary=0
WQ Write To DSS=0
Sorting and Armoring Iterations= 10
XS Update Threshold= 0.02
Bed Roughness Predictor= 0
Hydraulics Update Threshold= 0.02
Energy Slope Method= 1
Volume Change Method= 1
Sediment Retention Method= 0
Sediment TS Multiplier= 1
Warm Up Method= 0
XS Weighting Method= 0
Number of US Weighted Cross Sections= 1
Number of DS Weighted Cross Sections= 1
Upstream XS Weight=0
Main XS Weight=1
Downstream XS Weight=0
Number of DS XS's Weighted with US Boundary= 1
Upstream Boundary Weight= 1
Weight of XSs Associated with US Boundary= 0
Number of US XS's Weighted with DS Boundary= 1
Downstream Boundary Weight= 0.5
Weight of XSs Associated with DS Boundary= 0.5
Percentile Method= 0
Sediment Output Level= 3
Mass or Volume Output= 0
Output Increment Type= 1
Profile and TS Output Increment= 1
Transport Output Increment 1
XS Output Flag= 0
XS Output Increment= 10
Read HDF5 Sediment Hotstart= 0
Sediment Hotstart Type= 0
Write Gradation File= 0
Read Gradation Hotstart= 0
Write HDF5 File= 1
Write Binary Output= 1
Write DSS Sediment File= 0
DSS Sediment Output Type= 1
SV Curve= 0
Specific Gage Flag= 0
Subcell Erosion Methods= 0
Subcell Deposition Methods= 0
Advection Scheme= 1
Matrix Solver= 0
Implicit Weighting Factor= 1
Maximum Outer Loop Convergence Iterations= 5
Convergence Maximum Absolute= 0.001
Convergence RMSE= 0.0001
Grain Fractions Max Abs Error= 0.001
Max Subgrid Regions= 1
Max Subgrid Length Scale= 3.402823E+38
Initial Layer Thickness= 3.402823E+38
Min Layer Thickness= 3.402823E+38
Max Layer Thickness= 3.402823E+38
Number of Layers= 5

--- FIRSTFK_T1.f01 (steady flow) ---

Flow Title=Flow
Program Version=6.20
Number of Profiles= 1
Profile Names=P100yr
River Rch & RM=FIRSTFK_T1,Main,5724
     421
River Rch & RM=FIRSTFK_T1,Main,4804
     485
River Rch & RM=FIRSTFK_T1,Main,2733
     541
Boundary for River Rch & Prof#=FIRSTFK_T1,Main            , 1
Up Type= 0
Dn Type= 3
Dn Slope=0.03236
DSS Import GetInterval= 0
DSS Import GetPeak= 0
DSS Import FillOption= 0

--- FIRSTFK_T1.g01 (geometry) ---

Geom Title=Geometry
Program Version=6.20

River Reach=FIRSTFK_T1      ,Main
Reach XY= 30
2289427.75700001566710.1110000012289411.43799998       566630.25
2289291.99299999566486.5000000152289259.00700003566390.667000011
2288980.18800002566189.6250000152288759.03000003565874.347000018
2288563.55599999565970.7199999992288407.29400001565857.680999994
2288231.59999999565835.4580000042288139.58600001565878.513999999
     2287948.961565781.6390000132287725.00300004565829.903000012
2287573.96100001565732.333000019     2287389.586565732.333000019
     2287225.697565635.458000019      2287090.28565693.097000003
2286775.35000001565634.7640000132286603.47499998565684.417000011
2286497.22500002565618.0970000182286315.41600001565568.827999994
2286192.40200001565594.1180000162285847.79500002565492.862000018
2285625.38900003565588.3930000222285545.09900002565667.204999998
2285412.90300003565657.9290000052285354.42200004 565816.26700002
     2285130.859565816.0620000062284918.99200003565891.907000005
2284771.44599998 566015.189000012284662.75579192566046.628595874

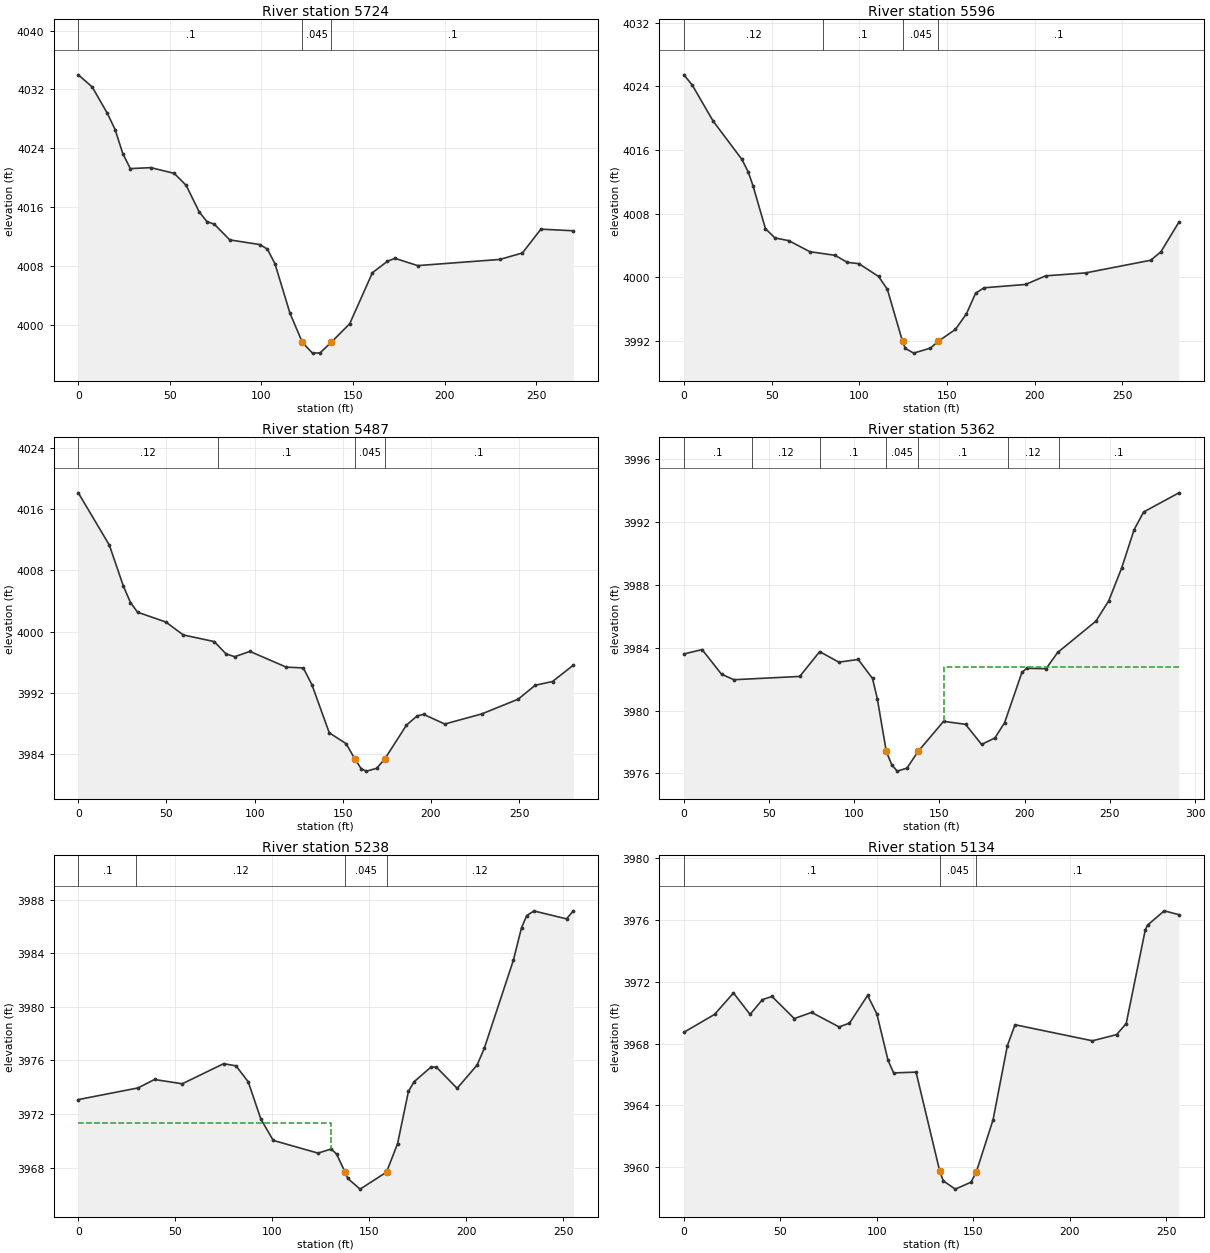
Type RM Length L Ch R = 1 ,5724    ,132.5,128.1,124.6
XS GIS Cut Line= 3
2289551.42042959566663.2025950682289463.20334468566689.474452857
2289288.92733547566726.970293629
#Sta/Elev= 30
       0 4033.99     7.6 4032.34    15.9 4028.74    20.1 4026.54    24.3 4023.28
    28.4 4021.23    39.6 4021.36    52.4 4020.58    58.9 4018.95      66 4015.35
    70.2 4014.03    74.3 4013.66    82.7 4011.53    99.2 4010.89   103.3 4010.26
   107.4 4008.28   115.6 4001.54  122.37 3997.57   127.9 3996.12     132 3996.15
   138.1 3997.59   148.2 4000.12   160.6 4007.06   168.8 4008.62   172.9 4009.02
   185.3 4008.03   230.2 4008.87   242.5 4009.75   252.6 4012.99   270.3 4012.77
#Mann= 3 ,-1,0
       0      .1       0  122.37    .045       0   138.1      .1       0
Bank Sta=122.37,138.1
XS Rating Curve= 0 ,0
Exp/Cntr=0.3,0.1

Type RM Length L Ch R = 1 ,5596    ,108.5,108.8,108.8
XS GIS Cut Line= 3
2289492.83379099566523.9544480922289453.42816501566524.939588741
2289259.35545708566670.740404853
#Sta/Elev= 30
       0 4025.45     4.7 4024.19    16.7 4019.63    33.1 4014.82    36.7 4013.24
    39.4 4011.52    46.5 4006.12    51.9 4004.96    59.8 4004.61    71.9 4003.22
    86.2 4002.77    93.1 4001.89    99.8 4001.72     111 4000.11     116  3998.5
  124.663991.949   126.2 3991.08     131 3990.48   140.5 3991.11   145.1 3991.98
   154.8 3993.46   161.1 3995.43   166.3 3998.01   171.1 3998.69   194.8 3999.11
   206.2 4000.19     229 4000.56   266.1 4002.15   271.9  4003.2   282.2 4006.94
#Mann= 4 ,-1,0
       0     .12       0   79.42      .1       0  124.66    .045       0
   145.1      .1       0
Bank Sta=124.66,145.1
XS Rating Curve= 0 ,0
Exp/Cntr(USF)=0,0
Exp/Cntr=0.3,0.1

Type RM Length L Ch R = 1 ,5487    ,127,125.5,123.2
XS GIS Cut Line= 3
2289449.81358021566435.7605610392289400.55654774566434.775420389
2289210.42440241566566.784267409
#Sta/Elev= 30
       0 4018.13    17.6 4011.31    25.6 4005.93    29.6 4003.81    33.6 4002.55
    49.7 4001.26    59.5 3999.58    77.1 3998.71    83.8  3997.1    88.7 3996.74
    97.3 3997.43   117.9 3995.38   127.6 3995.27   132.5 3993.07   142.3 3986.81
   151.9 3985.38   156.9 3983.36   160.5 3982.09   163.4  3981.8   169.1 3982.16
  173.763983.373   186.1 3987.81   192.1    3989   195.8 3989.21   207.8 3987.95
   228.8 3989.27   249.4 3991.19   259.1 3993.01   268.9  3993.5   280.7 3995.63
#Mann= 4 ,-1,0
       0     .12       0   79.27      .1       0   156.9    .045       0
  173.76      .1       0
Bank Sta=156.9,173.76
XS Rating Curve= 0 ,0
Exp/Cntr(USF)=0,0
Exp/Cntr=0.3,0.1

Type RM Length L Ch R = 1 ,5362    ,122.4,123.4,125.9
XS GIS Cut Line= 2
2289347.64453986566296.1561760082289144.70556608566504.020853031
#Sta/Elev= 30
       0 3983.61    10.7 3983.89    22.1 3982.32    29.4 3981.97      68 3982.18
    79.7 3983.76    90.9 3983.09   102.3 3983.26   110.7 3982.05   113.5 3980.77
   118.8  3977.4     122 3976.55   125.2 3976.15   130.9 3976.34  137.433977.401
   152.4 3979.32   165.3 3979.13   174.7 3977.85   182.5 3978.26   188.2 3979.23
   198.4 3982.44   201.2  3982.7   212.5 3982.67   219.4 3983.71   241.8  3985.7
   249.3 3986.99   256.9 3989.08   264.2 3991.52   269.8 3992.65   290.5 3993.87
#Mann= 7 ,-1,0
       0      .1       0      40     .12       0      80      .1       0
   118.8    .045       0  137.43      .1       0     190     .12       0
     220      .1       0
#XS Ineff= 2 , 0
                          152.69         3982.78
Permanent Ineff=
       F       F
Bank Sta=118.8,137.43
XS Rating Curve= 0 ,0
Exp/Cntr(USF)=0,0
Exp/Cntr=0.3,0.1

Type RM Length L Ch R = 1 ,5238    ,104.1,104.3,104.8
XS GIS Cut Line= 3
2289264.62289051566238.3228227252289226.49755474566268.869153286
2289065.43770385566397.887984364
#Sta/Elev= 30
       0 3973.08    30.8 3973.95    39.3 3974.58    53.6 3974.26    74.9 3975.76
    81.3  3975.6    87.6 3974.41    94.1 3971.63   100.5 3970.03   123.6 3969.08
   130.4 3969.39   133.2    3969137.53673967.653   138.9 3967.19   145.3 3966.39
   158.9 3967.66   164.6 3969.79   170.2 3973.69   173.1 3974.41   181.6 3975.48
   184.5 3975.52   195.3 3973.92   205.6 3975.66   209.3 3976.91   224.3 3983.49
   228.5 3985.92   231.2 3986.83   234.9 3987.17   251.7 3986.58   255.2 3987.18
#Mann= 4 ,-1,0
       0      .1       0      30     .12       0137.5367    .045       0
   158.9     .12       0
#XS Ineff= 2 , 0
          130.48 3971.34
Permanent Ineff=
       F       F
Bank Sta=137.5367,158.9
XS Rating Curve= 0 ,0
Exp/Cntr=0.3,0.1

Type RM Length L Ch R = 1 ,5134    ,164.5,165.2,165.7
XS GIS Cut Line= 2
 2289192.9774579566170.0581728842288986.09792153566321.769832892
#Sta/Elev= 30
       0 3968.73    15.9 3969.89    25.7 3971.28    34.3 3969.89    40.7 3970.85
    45.7 3971.05    57.2 3969.62    66.2 3970.02    80.4 3969.08    85.8 3969.32
    95.2 3971.12     100 3969.92   105.8 3966.91   108.7  3966.1   120.3 3966.15
   132.63959.725   134.4 3959.11   140.6 3958.57   148.8 3959.02   151.6 3959.71
   160.2 3963.06   167.6 3967.86   171.6 3969.22   211.7 3968.18   224.2 3968.58
   229.2  3969.3   239.1 3975.38   240.3 3975.68   248.9  3976.6   256.5 3976.35
#Mann= 3 ,-1,0
       0      .1       0   132.6    .045       0   151.6      .1       0
Bank Sta=132.6,151.6
XS Rating Curve= 0 ,0
Exp/Cntr(USF)=0,0
Exp/Cntr=0.3,0.1

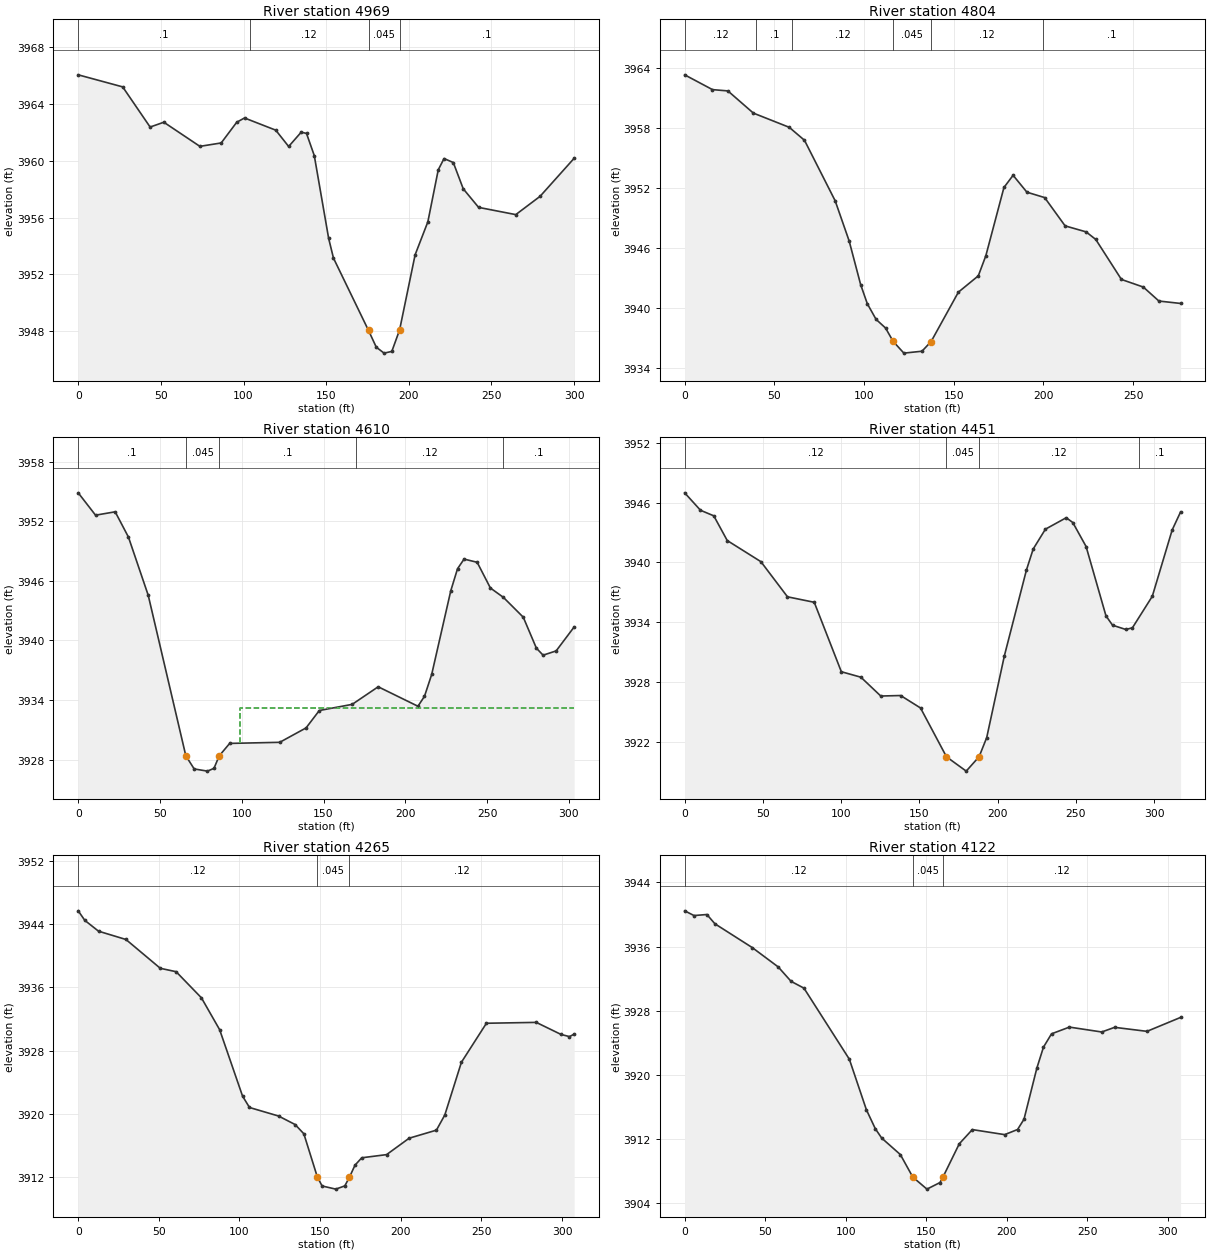
Type RM Length L Ch R = 1 ,4969    ,166.7,164.9,164.2
XS GIS Cut Line= 3
2289118.10676855566116.8605778172289047.17664179566097.157764829
2288854.08907451566215.374642757
#Sta/Elev= 30
       0 3966.06    26.9 3965.21    43.5 3962.38    51.8 3962.72    73.6 3961.02
    86.5 3961.26    95.9 3962.72   100.6 3963.02   119.5 3962.16   127.3 3961.01
   134.9 3962.02   138.1 3961.93   142.8 3960.37   151.5 3954.53   154.4 3953.15
   175.6 3948.05   180.3 3946.87     185 3946.45   189.7 3946.57   194.4 3948.08
   203.8 3953.38   211.5  3955.7   217.8 3959.37   221.3 3960.16   226.9 3959.88
   232.9 3958.03   242.2 3956.72   264.7 3956.21   279.4  3957.5     300 3960.18
#Mann= 4 ,-1,0
       0      .1       0  103.62     .12       0   175.6    .045       0
   194.4      .1       0
Bank Sta=175.6,194.4
XS Rating Curve= 0 ,0
Exp/Cntr(USF)=0,0
Exp/Cntr=0.3,0.1

Type RM Length L Ch R = 1 ,4804    ,199.3,194.3,183
XS GIS Cut Line= 2
2288968.36538984565935.5946983272288750.64930632566106.024030673
#Sta/Elev= 30
       0  3963.3    15.5 3961.82    24.1 3961.69    38.3 3959.47    58.3 3958.05
    66.8 3956.75    83.9  3950.7    91.7 3946.68    98.1 3942.32   101.8 3940.41
   106.7 3938.84     112 3937.97  116.233936.634   122.2 3935.46   132.3 3935.65
   137.4 3936.62   152.6 3941.56   163.7 3943.19   167.9  3945.2     178 3952.03
   183.1 3953.25   190.8 3951.56   200.7 3951.02   212.1 3948.19   223.8 3947.59
   229.2 3946.83   243.5 3942.83   255.7 3942.07   264.4 3940.67   276.5 3940.43
#Mann= 6 ,-1,0
       0     .12       0      40      .1       0      60     .12       0
  116.23    .045       0   137.4     .12       0     200      .1       0
Bank Sta=116.23,137.4
XS Rating Curve= 0 ,0
Exp/Cntr(USF)=0,0
Exp/Cntr=0.3,0.1

Type RM Length L Ch R = 1 ,4610    ,160.8,158.7,151.7
XS GIS Cut Line= 2
2288751.63444697 565798.660148062288719.12480554566100.113186777
#Sta/Elev= 30
       0 3954.85    10.6  3952.6    22.6 3952.94    30.7  3950.4    42.8 3944.54
   65.793928.385    70.9 3927.06      79 3926.84      83 3927.12   86.223928.382
    92.6 3929.63   123.2 3929.74   139.3 3931.19   147.4 3932.94   167.5 3933.56
   183.4 3935.33   207.7 3933.37   211.7 3934.37   216.1 3936.57   227.8 3945.01
   231.9 3947.21   235.9 3948.18   243.9 3947.86     252 3945.27     260 3944.32
   272.1 3942.33   280.1 3939.22   284.2 3938.51   292.2 3938.94   303.2 3941.35
#Mann= 5 ,-1,0
       0      .1       0   65.79    .045       0   86.22      .1       0
     170     .12       0     260      .1       0
#XS Ineff= 2 , 0
                           98.95         3933.16
Permanent Ineff=
       F       F
Bank Sta=65.79,86.22
XS Rating Curve= 0 ,0
Exp/Cntr(USF)=0,0
Exp/Cntr=0.3,0.1

Type RM Length L Ch R = 1 ,4451    ,175.7,185.7,196.3
XS GIS Cut Line= 3
2288625.53644385565791.7641635142288590.07138047565885.352525207
2288661.00150723566090.261780283
#Sta/Elev= 30
       0 3946.98    10.1 3945.23    18.6 3944.67    27.2 3942.19    48.7 3940.07
    65.7 3936.54    82.8 3935.99   100.1 3929.02   112.6 3928.47   125.3 3926.58
     138 3926.63   150.7 3925.38   167.33920.476   179.9 3919.04  188.153920.491
     193 3922.41   204.3 3930.63   218.4 3939.24   222.7 3941.34   230.5 3943.33
   243.8 3944.48     248    3944   256.5 3941.59   269.2 3934.63   273.4 3933.69
   281.9 3933.26   286.1 3933.43   298.8 3936.59   311.5 3943.25   316.9 3945.07
#Mann= 4 ,-1,0
       0     .12       0   167.3    .045       0  188.15     .12       0
  290.08      .1       0
Bank Sta=167.3,188.15
XS Rating Curve= 0 ,0
Exp/Cntr(USF)=0,0
Exp/Cntr=0.3,0.1

Type RM Length L Ch R = 1 ,4265    ,148.9,143.7,137.5
XS GIS Cut Line= 3
2288522.09667566565753.3436781872288481.70590904 565864.66457157
2288362.50389046566011.450528331
#Sta/Elev= 30
       0  3945.7     4.1 3944.49    12.6 3943.12    29.6 3942.07    50.9 3938.42
    60.7 3937.99    76.4 3934.68    87.7 3930.64   101.9 3922.23   106.2 3920.79
   124.2 3919.71   134.5 3918.63   139.9 3917.46   148.23912.032   151.2 3910.85
   159.7 3910.45   165.3 3910.86   168.2 3911.97   171.6 3913.48   175.8 3914.42
   191.2 3914.82   205.2  3916.9   222.1 3917.92   227.3 3919.84   237.6 3926.52
   253.1 3931.46     284 3931.57   299.4 3930.04   304.6 3929.77   307.5 3930.08
#Mann= 3 ,-1,0
       0     .12       0   148.2    .045       0   168.2     .12       0
Bank Sta=148.2,168.2
XS Rating Curve= 0 ,0
Exp/Cntr(USF)=0,0
Exp/Cntr=0.3,0.1

Type RM Length L Ch R = 1 ,4122    ,192.2,190.6,187.5
XS GIS Cut Line= 2
2288342.05622212565703.4104921692288311.19605163566009.990459646
#Sta/Elev= 30
       0 3940.46     5.8 3939.87    13.8    3940    18.8 3938.84      42 3935.87
    58.1 3933.46    66.1 3931.66    74.1 3930.81   102.3 3921.94   112.9 3915.63
   118.4 3913.28   122.4  3912.1     134 3910.04  141.713907.236   150.5 3905.73
   158.6 3906.55   160.4 3907.21   170.6 3911.39   178.7 3913.16   198.8 3912.53
   206.8 3913.17   210.8 3914.45   218.8 3920.84   222.9 3923.45   227.9 3925.11
     239 3925.95   259.1 3925.34   267.1 3925.92   287.2 3925.42   308.1 3927.16
#Mann= 3 ,-1,0
       0     .12       0  141.71    .045       0   160.4     .12       0
Bank Sta=141.71,160.4
XS Rating Curve= 0 ,0
Exp/Cntr(USF)=0,0
Exp/Cntr=0.3,0.1

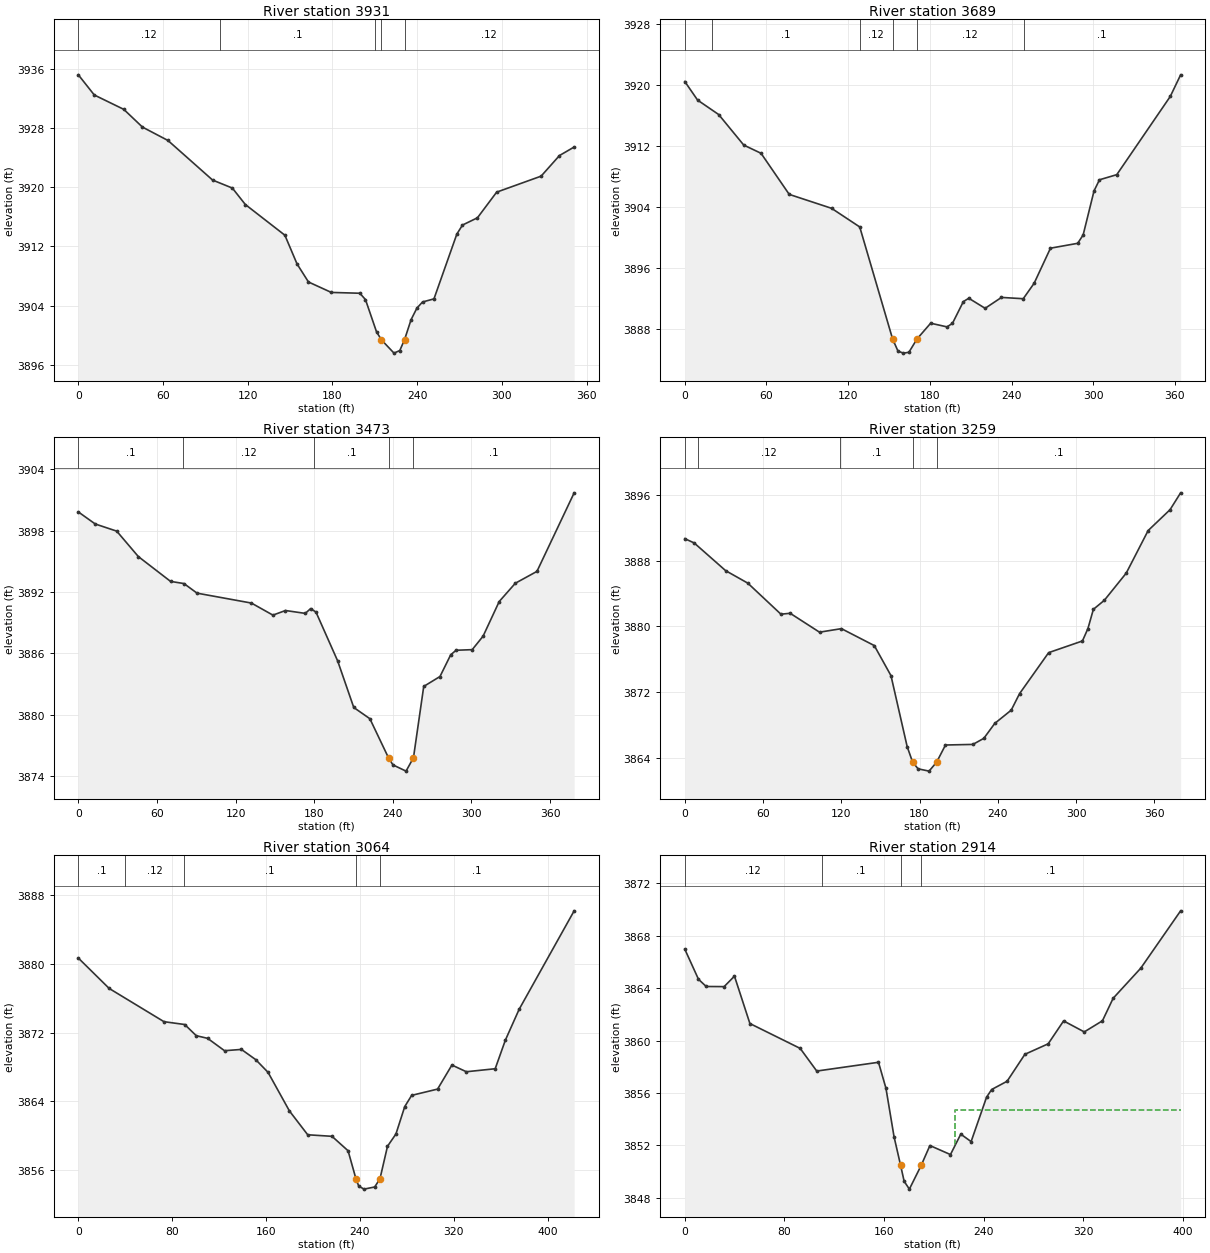
Type RM Length L Ch R = 1 ,3931    ,241.8,242.4,243.1
XS GIS Cut Line= 3
2288220.64363695565679.4581294822288143.80266629565808.511554554
2288172.37174512566007.509965733
#Sta/Elev= 30
       0 3935.16    11.3 3932.44    32.2  3930.5    45.4 3928.11    63.5  3926.3
    95.1 3920.96   109.1 3919.88   118.3 3917.66   146.3 3913.52   154.9 3909.65
     163 3907.21   179.2  3905.8   199.4 3905.69   203.4 3904.83   211.2 3900.49
   214.7  3899.4   223.6 3897.61   227.7 3897.96  231.093899.442   235.7 3902.13
   239.8 3903.68   243.8 3904.51   251.9 3904.93   268.1 3913.67   272.1 3914.89
   282.7 3915.87   296.3 3919.33   327.8 3921.49   340.8 3924.27   351.2 3925.42
#Mann= 5 ,-1,0
       0     .12       0     100      .1       0   210.2     .12       0
   214.7    .045       0  231.09     .12       0
Bank Sta=214.7,231.09
XS Rating Curve= 0 ,0
Exp/Cntr(USF)=0,0
Exp/Cntr=0.3,0.1

Type RM Length L Ch R = 1 ,3689    ,213.7,215.9,218.5
XS GIS Cut Line= 3
2288019.67494447    565649.903912287937.90827057 565749.40311559
2287939.87855187565984.851730797
#Sta/Elev= 30
       0 3920.46     9.4 3918.02    24.9 3916.12    43.3 3912.11      56 3911.03
    76.7 3905.63   107.8  3903.8   128.5 3901.35   152.6 3886.65   156.6 3885.03
   160.6 3884.77   164.6 3884.88   170.6 3886.64   180.6  3888.7   192.6 3888.22
   196.6 3888.68   204.6 3891.54   208.6 3891.98   220.6 3890.66   232.6 3892.09
   248.6 3891.92   256.6 3893.95   268.6 3898.56   288.6  3899.2   292.6  3900.3
   300.6 3906.09   304.6 3907.55   317.3 3908.22   356.6  3918.5   364.2 3921.34
#Mann= 6 ,-1,0
       0     .12       0      20      .1       0  128.79     .12       0
   152.6    .045       0   170.6     .12       0  248.79      .1       0
Bank Sta=152.6,170.6
XS Rating Curve= 0 ,0
Exp/Cntr(USF)=0,0
Exp/Cntr=0.3,0.1

Type RM Length L Ch R = 1 ,3473    ,213.2,213.3,214.9
XS GIS Cut Line= 2
2287788.64634684565592.6449799912287701.34109548565960.784883262
#Sta/Elev= 30
       0 3899.83    12.9 3898.65    29.3 3897.95    45.8 3895.46    70.4 3893.03
    80.6 3892.82    90.6 3891.88   132.1 3890.91   148.5 3889.73   158.1 3890.18
   173.2  3889.9   177.3 3890.37   181.4 3890.02   197.9 3885.25   210.2 3880.69
   222.5 3879.59   236.8 3875.74   240.1 3875.07   250.1 3874.46  255.773875.775
   263.6 3882.75     276 3883.72   284.2 3885.85   288.3 3886.29   300.6 3886.35
   308.9 3887.67   321.2 3891.06   333.5 3892.85     350 3894.01   378.4  3901.7
#Mann= 5 ,-1,0
       0      .1       0      80     .12       0     180      .1       0
   236.8    .045       0  255.77      .1       0
Bank Sta=236.8,255.77
XS Rating Curve= 0 ,0
Exp/Cntr(USF)=0,0
Exp/Cntr=0.3,0.1

Type RM Length L Ch R = 1 ,3259    ,193.1,195.2,197.6
XS GIS Cut Line= 3
2287648.27691964565575.0332206462287578.33193354565644.978206753
2287492.62469704565912.936463391
#Sta/Elev= 30
       0 3890.67     7.2 3890.15    31.3 3886.78    48.3 3885.26    73.7 3881.48
    80.8 3881.59   103.3 3879.29   120.1 3879.72   145.3 3877.66   158.1    3874
   170.5 3865.37   174.7 3863.47   178.9 3862.66   187.3 3862.38   193.1 3863.47
   199.9 3865.56   220.9 3865.63   229.3 3866.37   237.7 3868.19   250.3  3869.8
   256.7 3871.81     279  3876.8   304.9 3878.22   309.1 3879.72   313.3 3882.07
   321.7 3883.17   338.5 3886.48   355.3 3891.66   372.1  3894.2   380.2 3896.25
#Mann= 5 ,-1,0
       0      .1       0      10     .12       0  118.92      .1       0
   174.7    .045       0   193.1      .1       0
Bank Sta=174.7,193.1
XS Rating Curve= 0 ,0
Exp/Cntr(USF)=0,0
Exp/Cntr=0.3,0.1

Type RM Length L Ch R = 1 ,3064    ,151.5,150,148
XS GIS Cut Line= 4
2287522.75122566565542.2216075252287418.47730267565614.468427903
2287337.54478357 565764.863394292287364.12351809565886.920519745
#Sta/Elev= 30
       0  3880.7    26.3 3877.16      73 3873.29    90.7 3872.96   100.5 3871.66
   110.2 3871.35   124.6 3869.91     139 3870.06   151.2 3868.87   161.7 3867.39
   179.9  3862.9   195.5 3860.12   216.2 3859.94   229.9 3858.26  236.56 3855.02
     239 3854.14   243.5 3853.79   252.6 3854.04   257.1    3855   263.5 3858.78
   270.7 3860.21   278.2  3863.4   284.1 3864.71   306.2 3865.44   318.4 3868.24
   330.7 3867.46   355.3 3867.81     364 3871.15   375.7 3874.73   422.6  3886.2
#Mann= 5 ,-1,0
       0      .1       0      40     .12       0      90      .1       0
  236.56    .045       0   257.1      .1       0
Bank Sta=236.56,257.1
XS Rating Curve= 0 ,0
Exp/Cntr(USF)=0,0
Exp/Cntr=0.3,0.1

Type RM Length L Ch R = 1 ,2914    ,181.8,180.8,179
XS GIS Cut Line= 2
2287282.48839162 565462.562909952287182.59240956565848.125720228
#Sta/Elev= 30
       0 3866.98      11 3864.68    17.2 3864.13    31.6 3864.12    39.9 3864.92
    52.3  3861.3    92.7  3859.4     106 3857.67   155.6 3858.34   161.6 3856.35
   168.1 3852.65   173.3 3850.49   176.2 3849.25   180.4 3848.65  189.863850.458
   196.9 3851.98   213.4 3851.29   221.7 3852.85     230 3852.28   242.4 3855.67
   246.5 3856.26   258.9 3856.89   273.2 3858.95   291.9 3859.75   304.3  3861.5
   320.9 3860.66   335.5 3861.51   344.1 3863.23   366.3 3865.53   398.3 3869.91
#Mann= 4 ,-1,0
       0     .12       0     110      .1       0   173.3    .045       0
  189.86      .1       0
#XS Ineff= 2 , 0
                          217.21         3854.67
Permanent Ineff=
       F       F
Bank Sta=173.3,189.86
XS Rating Curve= 0 ,0
Exp/Cntr(USF)=0,0
Exp/Cntr=0.3,0.1

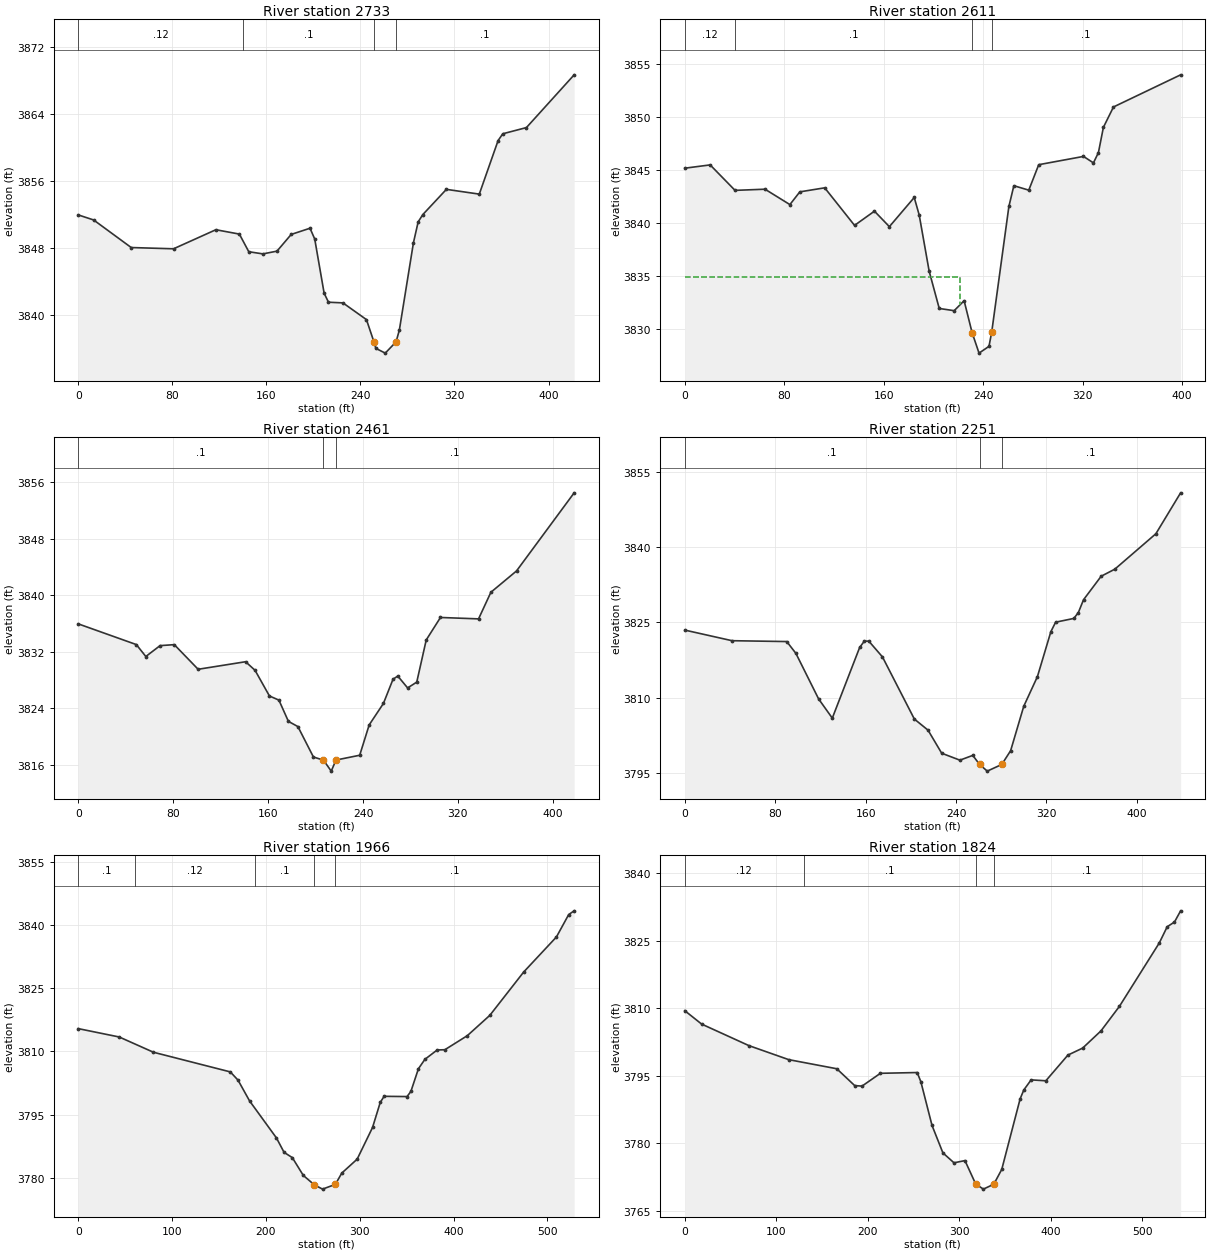
Type RM Length L Ch R = 1 ,2733    ,120.9,122.1,121.7
XS GIS Cut Line= 2
2287077.88048364565432.187826483 2287067.0439365565853.828024426
#Sta/Elev= 30
       0 3851.91      13 3851.31      45 3848.01      81 3847.86     117 3850.14
     137 3849.62     145 3847.51     157 3847.25     169 3847.58   181.1 3849.58
   197.1 3850.32   201.1 3849.03   209.1 3842.55   212.8 3841.47   225.1 3841.39
   245.1 3839.39  251.573836.685   253.1 3835.95   261.1 3835.38   270.3 3836.73
   273.1 3838.14   285.1  3848.6   289.1 3851.08   293.1 3851.96   313.1 3854.97
   341.1  3854.4   357.1 3860.81   361.1 3861.62   381.2 3862.36   421.8 3868.67
#Mann= 4 ,-1,0
       0     .12       0     140      .1       0  251.57    .045       0
   270.3      .1       0
Bank Sta=251.57,270.3
XS Rating Curve= 0 ,0
Exp/Cntr(USF)=0,0
Exp/Cntr=0.3,0.1

Type RM Length L Ch R = 1 ,2611    ,149.5,149.9,150.9
XS GIS Cut Line= 2
 2286962.4889959 565432.773190452286947.37693233565831.182139261
#Sta/Elev= 30
       0  3845.2    20.4 3845.51    40.4 3843.11    64.5 3843.22    84.5 3841.77
    92.5 3842.97   112.5 3843.35   136.5 3839.81   152.5 3841.15   164.5 3839.69
   184.5 3842.44   188.5 3840.78   196.5 3835.49   204.6 3831.98   216.6 3831.77
   224.6 3832.71     231 3829.71   236.6 3827.77   244.6 3828.41  246.783829.739
   260.6 3841.59   264.6 3843.55   276.6 3843.13   284.6 3845.53   320.6 3846.31
   328.6  3845.7   332.6 3846.67   336.6 3849.05   344.7 3850.97   398.7    3854
#Mann= 4 ,-1,0
       0     .12       0      40      .1       0     231    .045       0
  246.78      .1       0
#XS Ineff= 2 , 0
          221.56 3834.99
Permanent Ineff=
       F       F
Bank Sta=231,246.78
XS Rating Curve= 0 ,0
Exp/Cntr(USF)=0,0
Exp/Cntr=0.3,0.1

Type RM Length L Ch R = 1 ,2461    ,209.1,210.3,213.5
XS GIS Cut Line= 2
2286821.31095672565428.412518477 2286795.9091611565845.677795543
#Sta/Elev= 30
       0 3835.93    48.9    3833    56.9 3831.31    68.9 3832.85    80.9 3832.99
     101  3829.5     141 3830.57     149 3829.35   161.1 3825.72   169.1 3825.13
   177.1 3822.12   185.1 3821.38   198.2 3817.07  206.683816.625   213.2 3815.07
   217.2 3816.63   217.2 3816.64   237.2 3817.32   245.2 3821.62   257.2 3824.66
   265.3 3828.09   269.3 3828.54   277.6 3826.86   285.3 3827.68   293.3 3833.66
   305.3 3836.84   337.4 3836.64   347.8 3840.41   369.4 3843.43     418  3854.5
#Mann= 3 ,-1,0
       0      .1       0  206.68    .045       0   217.2      .1       0
Bank Sta=206.68,217.2
XS Rating Curve= 0 ,0
Exp/Cntr(USF)=0,0
Exp/Cntr=0.3,0.1

Type RM Length L Ch R = 1 ,2251    ,285.5,285.3,286.8
XS GIS Cut Line= 2
2286640.73799672565419.6625811982286585.96435012565854.893228921
#Sta/Elev= 30
       0 3823.47    41.8 3821.36    90.2 3821.19    98.3 3818.84   118.4 3809.78
   130.5 3805.96   154.7 3820.01   158.8 3821.26   162.8 3821.28   174.9 3818.13
   203.1 3805.78   215.2 3803.57   227.3 3798.98   243.4  3797.6   254.8 3798.55
   260.8 3796.76   267.6 3795.42  280.473796.747   288.3 3799.49   299.9 3808.32
     312 3814.22   323.9 3823.16   328.1 3825.04   344.2 3825.79   348.2 3826.95
   352.8 3829.51   368.4 3834.18   380.5 3835.59   416.8 3842.63   438.7 3850.77
#Mann= 3 ,-1,0
       0      .1       0   260.8    .045       0  280.47      .1       0
Bank Sta=260.8,280.47
XS Rating Curve= 0 ,0
Exp/Cntr(USF)=0,0
Exp/Cntr=0.3,0.1

Type RM Length L Ch R = 1 ,1966    ,143.7,141.7,140.2
XS GIS Cut Line= 4
2286510.27201786565396.8456867152286371.79943763565473.589526361
2286330.09082913565662.1124367952286340.10089517565838.956936849
#Sta/Elev= 30
       0 3815.37    43.6 3813.39    80.1 3809.77     162 3805.11   170.2 3803.16
   182.5 3798.24   211.2 3789.44   219.3 3786.03   228.1 3784.78   239.8 3780.56
   251.6 3778.32   260.3 3777.31     274 3778.44   280.8 3781.11   297.2 3784.42
   313.6 3791.93   321.8 3797.86   325.9 3799.32   350.4 3799.26   354.5 3800.49
   362.5 3805.86   369.4 3808.09   382.5 3810.31   390.7 3810.37   414.6  3813.7
   438.6 3818.52   474.7  3828.8   509.6 3837.11   522.7 3842.43   528.5 3843.31
#Mann= 5 ,-1,0
       0      .1       0      60     .12       0  188.32      .1       0
   251.6    .045       0     274      .1       0
Bank Sta=251.6,274
XS Rating Curve= 0 ,0
Exp/Cntr(USF)=0,0
Exp/Cntr=0.3,0.1

Type RM Length L Ch R = 1 ,1824    ,227.4,229.9,231.7
XS GIS Cut Line= 3
2286379.98763626565353.091400687 2286228.8670005565443.763782141
2286194.52140147565807.827131917
#Sta/Elev= 30
       0 3809.46    18.4 3806.49    70.1 3801.71   113.6  3798.6   166.1 3796.58
   185.7 3792.84   193.7 3792.73   213.8 3795.57     254 3795.74     258  3793.7
   270.2    3784   282.1 3777.91   294.2 3775.71   306.2  3776.2   317.93771.017
   326.3 3769.87   337.73770.955   346.4 3774.24   366.5  3789.9   370.5 3791.87
   378.5 3794.11   394.6 3793.91   418.7 3799.61   434.8 3801.16   454.9 3804.99
     475 3810.42   518.6  3824.5   527.2 3828.08   535.2 3829.14   541.9 3831.62
#Mann= 4 ,-1,0
       0     .12       0     130      .1       0   317.9    .045       0
   337.7      .1       0
Bank Sta=317.9,337.7
XS Rating Curve= 0 ,0
Exp/Cntr(USF)=0,0
Exp/Cntr=0.3,0.1

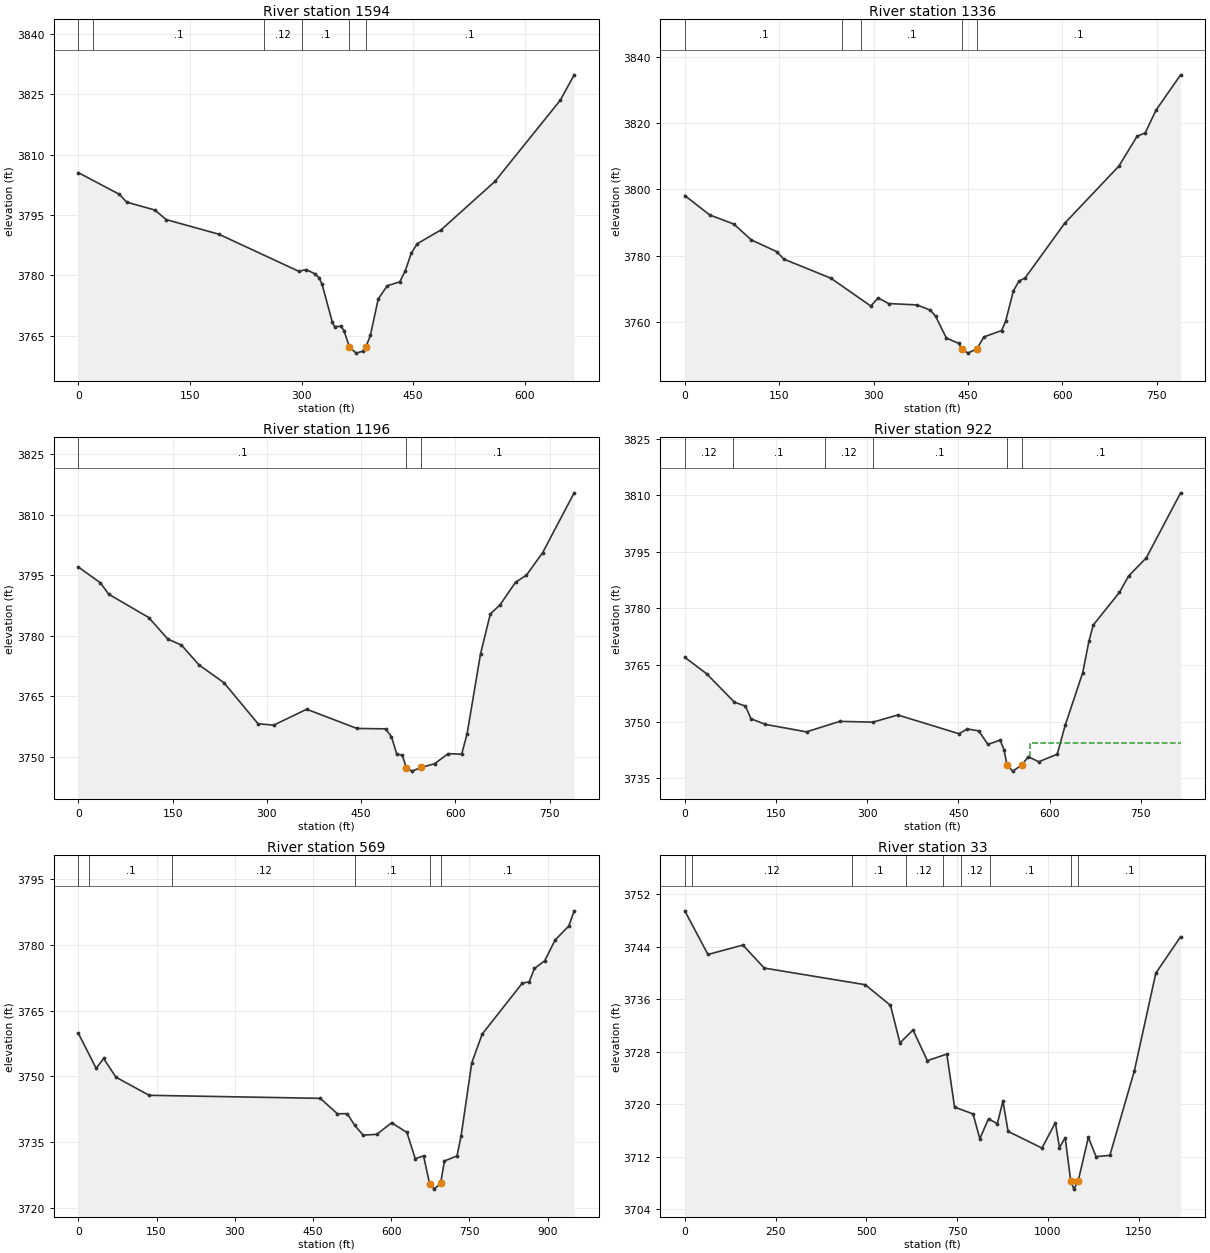
Type RM Length L Ch R = 1 ,1594    ,265.1,257.8,249.9
XS GIS Cut Line= 4
2286278.07322811565303.7258969062286011.45765701565483.276908517
2285986.28373693565563.3757451492286010.37460396565823.230693294
#Sta/Elev= 30
       0  3805.5    55.3  3800.1      65 3798.17   102.9 3796.21     118 3793.84
   188.8 3790.21   296.4 3780.98   306.1 3781.42   317.7 3780.39   323.4 3779.44
   327.6 3777.77   341.5 3768.27   344.4 3767.23   352.8 3767.34     357 3766.28
  364.37 3762.17   373.4 3760.66   382.1 3761.13   386.6 3762.23   392.6 3765.13
   403.1 3774.14   415.2  3777.4   431.9 3778.36   439.3 3781.06   447.4 3785.44
   455.4 3787.83   487.6 3791.29   559.9 3803.32   647.8  3823.5   666.4  3829.8
#Mann= 6 ,-1,0
       0     .12       0      20      .1       0     250     .12       0
     300      .1       0  364.37    .045       0   386.6      .1       0
Bank Sta=364.37,386.6
XS Rating Curve= 0 ,0
Exp/Cntr(USF)=0,0
Exp/Cntr=0.3,0.1

Type RM Length L Ch R = 1 ,1336    ,140.8,140.8,140.5
XS GIS Cut Line= 3
2285965.80607133565192.6582635382285720.88574855565445.208604843
2285873.42536138565854.008411083
#Sta/Elev= 30
       0 3798.12    39.7 3792.26    77.9 3789.52   105.8 3784.73     146 3781.23
   157.5 3778.95   232.2 3773.21   295.7 3764.81   307.2 3767.28   323.9 3765.57
   368.9 3765.16   390.2 3763.58   398.7 3761.73   415.8 3755.17   435.2 3753.58
  440.333751.957     450 3750.63   464.2 3751.94   475.6 3755.53   503.6 3757.43
     510 3760.26   522.2 3769.35   531.1 3772.32   540.9 3773.28   603.7 3789.73
   690.1 3807.02   718.9 3815.98   731.8 3816.99   748.8 3823.78   788.1 3834.49
#Mann= 5 ,-1,0
       0      .1       0     250     .12       0     280      .1       0
  440.33    .045       0   464.2      .1       0
Bank Sta=440.33,464.2
XS Rating Curve= 0 ,0
Exp/Cntr(USF)=0,0
Exp/Cntr=0.3,0.1

Type RM Length L Ch R = 1 ,1196    ,275.5,273.6,268.4
XS GIS Cut Line= 3
2285870.11277801565150.0251067042285598.62250635565522.604722246
2285718.38307802565827.891540864
#Sta/Elev= 30
       0 3797.01    35.1  3793.1    48.4 3790.26     112 3784.49   142.5 3779.13
     164 3777.67     192 3772.74   231.6 3768.34     286 3758.15   310.8 3757.81
   363.3 3761.75   443.3 3756.99   488.9 3756.89   498.2 3754.96   506.7  3750.6
   515.3 3750.39     5223747.256     531 3746.41   545.53747.313   566.9 3748.25
   588.4 3750.74   609.9  3750.6   618.5 3755.62   639.9 3775.46   655.5 3785.37
     671 3787.64   695.6 3793.23     713 3794.99   738.8 3800.58   788.9  3815.4
#Mann= 3 ,-1,0
       0      .1       0     522    .045       0   545.5      .1       0
Bank Sta=522,545.5
XS Rating Curve= 0 ,0
Exp/Cntr(USF)=0,0
Exp/Cntr=0.3,0.1

Type RM Length L Ch R = 1 ,922     ,342.9,352.6,357.9
XS GIS Cut Line= 3
2285588.39944243 565201.690507592285358.56042709565620.909939402
2285563.41878812565889.139666007
#Sta/Elev= 30
       0 3767.05    35.9 3762.71    81.5 3755.18    99.8 3754.13   108.9 3750.78
   132.4 3749.29   200.2 3747.31   254.9 3750.08   309.6 3749.89   350.4 3751.78
     451 3746.81   464.7 3748.08   483.5 3747.57   498.6 3743.98   518.7 3745.12
   525.1 3742.57   530.23738.422   539.4  3736.9     5543738.465     565 3740.72
   582.2 3739.38   612.6 3741.38   625.7 3749.04   654.6 3763.01   664.7 3771.29
   671.9 3775.62     715 3784.29   730.1 3788.63   759.1 3793.41   815.6 3810.65
#Mann= 6 ,-1,0
       0     .12       0      80      .1       0     230     .12       0
     310      .1       0   530.2    .045       0     554      .1       0
#XS Ineff= 2 , 0
                          567.44         3744.27
Permanent Ineff=
       F       F
Bank Sta=530.2,554
XS Rating Curve= 0 ,0
Exp/Cntr(USF)=0,0
Exp/Cntr=0.3,0.1

Type RM Length L Ch R = 1 ,569     ,538.2,536.8,536.7
XS GIS Cut Line= 4
2285490.19216306  565216.07574552285166.62364521 565732.53227536
2285160.85547573565860.1096217052285291.30215253566029.461447726
#Sta/Elev= 30
       0 3759.85    34.2 3751.83    48.5 3754.09    72.1 3749.83   135.8 3745.69
   463.9    3745   496.9 3741.48   515.8 3741.51     530 3738.84   546.3  3736.6
   572.4 3736.79   600.8 3739.42   630.1 3737.23   646.1 3731.24   662.1 3731.86
  673.63 3725.57   682.2 3724.29   694.73725.575   702.2 3730.71   726.2 3731.86
   734.2 3736.48   754.5 3753.08   774.5 3759.65   851.5 3771.28   864.7 3771.57
   874.8 3774.64   894.3 3776.36   914.3  3781.1   940.5 3784.29   950.9 3787.77
#Mann= 6 ,-1,0
       0     .12       0      20      .1       0     180     .12       0
     530      .1       0  673.63    .045       0   694.7      .1       0
Bank Sta=673.63,694.7
XS Rating Curve= 0 ,0
Exp/Cntr(USF)=0,0
Exp/Cntr=0.3,0.1

Type RM Length L Ch R = 1 ,33      ,,,
XS GIS Cut Line= 4
2285389.85853676565233.5784205662284694.28310524566016.373316091
2284696.10818119  566084.86602582284927.15189615566181.010821307
#Sta/Elev= 30
       0 3749.43    63.7 3742.79     160 3744.22   219.1 3740.72   497.1 3738.19
   566.7 3735.05   592.7 3729.34   628.8  3731.3   668.3 3726.63   721.9 3727.64
   743.2 3719.57   794.2 3718.53   812.8 3714.76   836.7 3717.79     861 3717.04
   876.4  3720.5   890.6 3715.88     984 3713.34  1020.9  3717.2  1032.3 3713.41
    1048 3714.931063.1523708.351    1072 3707.09 1083.96 3708.38  1111.8 3714.97
  1133.1 3712.03  1171.1 3712.23  1238.4 3725.06  1297.7 3739.96    1366 3745.49
#Mann= 9 ,-1,0
       0      .1       0      20     .12       0     460      .1       0
     610     .12       0     710      .1       0     760     .12       0
     840      .1       01063.152    .045       0 1083.96      .1       0
Bank Sta=1063.152,1083.96
XS Rating Curve= 0 ,0
Exp/Cntr(USF)=0,0
Exp/Cntr=0.3,0.1
LCMann Table=0

Chan Stop Cuts=-1
Use User Specified Reach Order=0
Composite Channel Slope=5